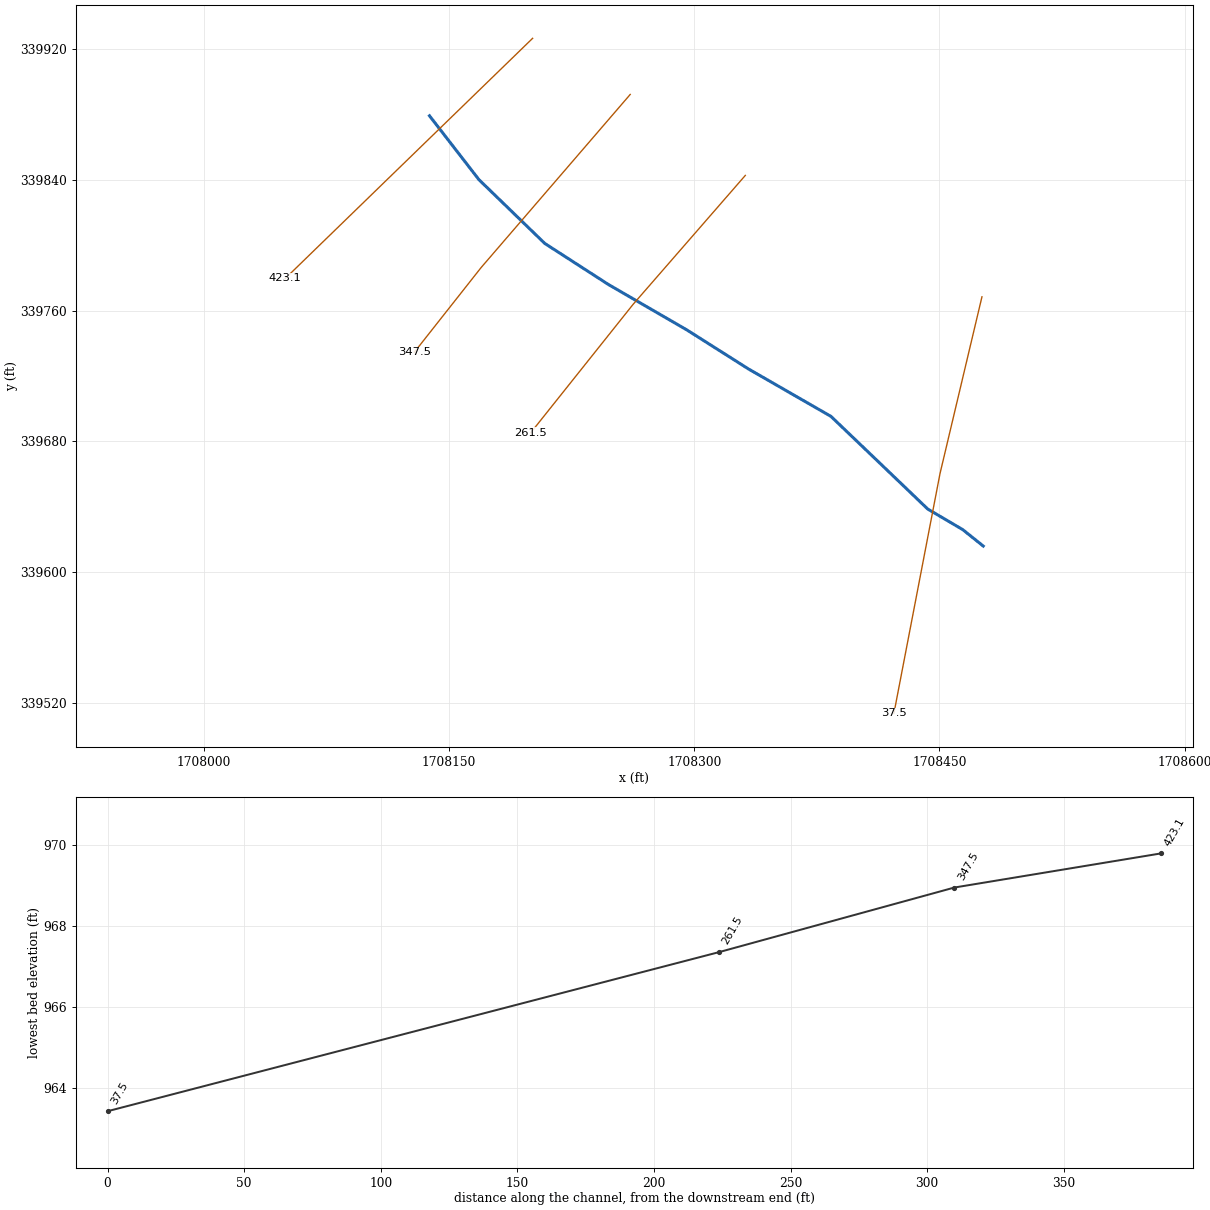
--- BALDWINFRK.prj (project) ---

Proj Title=BALDWINFRK
Current Plan=p01
Default Exp/Contr=0,0
English Units
Geom File=g01
Flow File=f01
Plan File=p01
BEGIN DESCRIPTION:
END DESCRIPTION:
DSS Export Rating Curves= 0
DSS Export Rating Curve Sorted= 0
DSS Export Volume Flow Curves= 0
DXF OffsetX= 0
DXF OffsetY= 0
DXF ScaleX= 0
DXF ScaleY= 0

--- BALDWINFRK.p01 (plan) ---

Plan Title=Floodplain
Program Version=4.00
Geom File=g01
Flow File=f01
K Sum by GR=0
Std Step Tol=0.01
Critical Tol=0.01
Num of Std Step Trials=20
Max Error Tol=0.3
Flow Tol Ratio=0.001
Split Flow NTrial=30
Split Flow Tol=0.02
Split Flow Ratio=0.02
Log Output Level=0
Friction Slope Method=1
Unsteady Friction Slope Method=2
Unsteady Bridges Friction Slope Method=1
Global Log Level=0
CheckData=False
Run HTab=0
Run UNet=0
Run PostProcess=0
UNET Theta=0
UNET Theta Warmup=0
UNET ZTol=0
UNET ZSATol=0
UNET MxIter=0
UNET MaxInSteps=0
UNET DtIC=0
UNET DtMin=0
UNET MaxCRTS=0
UNET WFStab=0
UNET SFStab=0
UNET WFX=0
UNET SFX=0
UNET DSS MLevel=0
UNET DZMax Abort=0
UNET Convert EG Bridges=0
UNET Use Existing IB Tables=0
UNET Froude Limit=0
UNET Froude Power=0
Write IC File=0
Echo Input=False
Echo Output=False
Write Detailed=0

--- BALDWINFRK.f01 (steady flow) ---

Flow Title=NFF Regression Equation
Program Version=4.00
Number of Profiles=1
Profile Names=P100yr
River Rch & RM=BALDWINFRK,Main      ,423.1
888.6882
River Rch & RM=BALDWINFRK,Main      ,261.5
891.6806
Boundary for River Rch & Prof#=BALDWINFRK,Main      ,1
Up Type=0
Dn Type=3
Dn Slope=0.015683

--- BALDWINFRK.g01 (geometry) ---

Geom Title=USGS 10m DEM
Program Version=4.10

River Reach=BALDWINFRK      ,Main
Reach XY= 11
     1708137.943      339879.275     1708168.176      339840.224
     1708208.487      339801.172     1708247.539      339775.978
     1708295.409      339748.264       1708333.2      339724.329
      1708383.59      339695.355     1708412.563      339667.641
     1708442.797      339638.667     1708464.212       339626.07
     1708476.809      339615.992

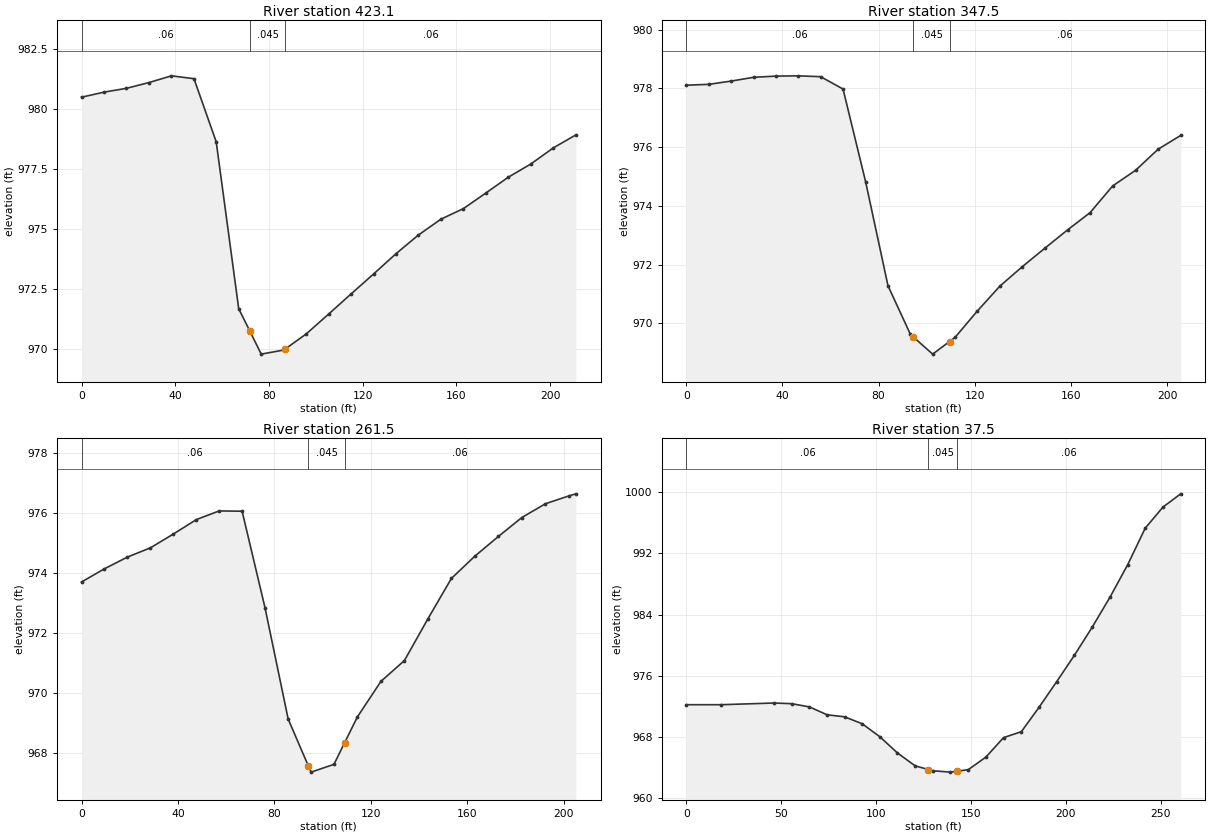
Type RM Length L Ch R = 1 ,423.1   ,73.6,75.6,77.6
XS GIS Cut Line= 2
     1708201.039      339926.683     1708049.677       339779.73
#Sta/Elev= 25
       0  980.49     9.6   980.7    19.2  980.86    28.8   981.1    38.4  981.38
      48  981.26    57.5  978.63    67.1  971.68    71.9  970.74    76.7  969.79
    86.3  969.96    86.9     970    95.9  970.63   105.5  971.46   115.1   972.3
   124.7  973.13   134.2  973.97   143.8  974.75   153.4  975.41     163  975.85
   172.6   976.5   182.2  977.16   191.8  977.71   201.4  978.38     211  978.92
#Mann= 3 , 0 , 0
       0     .06       0    71.9    .045       0    86.9     .06       0
Bank Sta=71.9,86.9
XS Rating Curve= 0 ,0
Exp/Cntr=0.3,0.1

Type RM Length L Ch R = 1 ,347.5   ,86.3,86.1,86.8
XS GIS Cut Line= 3
     1708260.758      339892.333     1708169.541      339786.426
       1708128.7      339734.658
#Sta/Elev= 25
       0  978.11     9.3  978.14    18.6  978.25      28  978.38    37.3  978.42
    46.6  978.43    55.9   978.4    65.2  977.98    74.6  974.82    83.9  971.28
    93.2  969.63    94.5  969.53   102.5  968.95   109.5  969.38   111.8  969.52
   121.1  970.42   130.5  971.27   139.8  971.93   149.2  972.56   158.6  973.18
     168  973.77   177.4  974.68   186.9  975.21   196.3  975.93   205.7   976.4
#Mann= 3 , 0 , 0
       0     .06       0    94.5    .045       0   109.5     .06       0
Bank Sta=94.5,109.5
XS Rating Curve= 0 ,0
Exp/Cntr=0.3,0.1

Type RM Length L Ch R = 1 ,261.5   ,210.9,223.9,235.5
XS GIS Cut Line= 4
     1708331.206      339842.805     1708262.477      339763.828
      1708201.75      339687.657     1708199.915      339685.355
#Sta/Elev= 25
       0   973.7     9.5  974.14      19  974.53    28.6  974.84    38.1   975.3
    47.6  975.78    57.1  976.07    66.6  976.06    76.1  972.84    85.7  969.13
    94.1  967.56    95.2  967.36   104.7  967.62   109.1  968.34   114.4   969.2
   124.2  970.39   133.9  971.08   143.7  972.48   153.4  973.82   163.1  974.56
   172.9  975.22   182.6  975.85   192.4  976.31   202.1  976.57     205  976.64
#Mann= 3 , 0 , 0
       0     .06       0    94.1    .045       0   109.1     .06       0
Bank Sta=94.1,109.1
XS Rating Curve= 0 ,0
Exp/Cntr=0.3,0.1

Type RM Length L Ch R = 1 ,37.5    ,47.4,37.3,27.8
XS GIS Cut Line= 3
     1708476.013      339768.521     1708450.333      339660.302
     1708422.131      339513.602
#Sta/Elev= 28
       0  972.24    18.5  972.24    46.3  972.46    55.6  972.37    64.9  971.95
    74.2  970.92    83.4  970.66    92.7  969.75     102  968.06   111.2  965.96
   120.6  964.26   127.6  963.78   129.9  963.62   139.2  963.44   142.6  963.56
   148.6  963.76   157.9   965.4   167.2  967.94   176.6  968.72   185.9  971.89
   195.2  975.24   204.6   978.7   213.9  982.34   223.3  986.26   232.6  990.48
   241.9  995.28   251.3  998.04   260.6  999.76
#Mann= 3 , 0 , 0
       0     .06       0   127.6    .045       0   142.6     .06       0
Bank Sta=127.6,142.6
XS Rating Curve= 0 ,0
Exp/Cntr=0.3,0.1

Chan Stop Cuts=-1
Use User Specified Reach Order=0
Composite Channel Slope=5